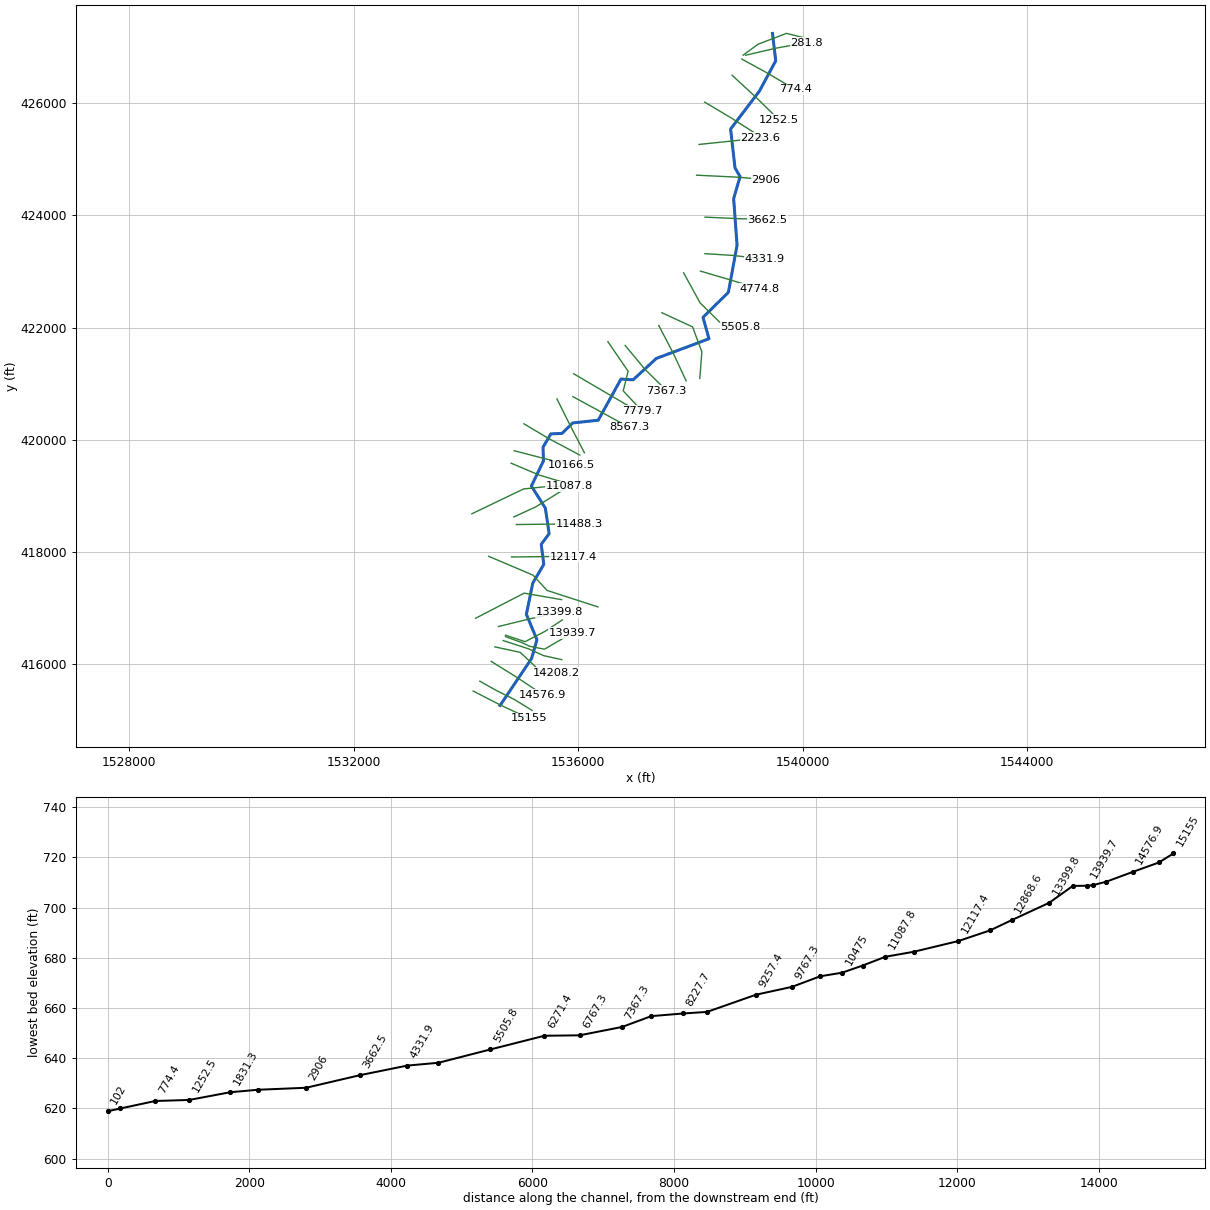
--- GRNBRIERCR.prj (project) ---

Proj Title=GRNBRIERCR
Current Plan=p01
Default Exp/Contr=0,0
English Units
Geom File=g01
Flow File=f01
Plan File=p01
BEGIN DESCRIPTION:
END DESCRIPTION:
DSS Export Rating Curves= 0
DSS Export Rating Curve Sorted= 0
DSS Export Volume Flow Curves= 0
DXF OffsetX= 0
DXF OffsetY= 0
DXF ScaleX= 0
DXF ScaleY= 0

--- GRNBRIERCR.p01 (plan) ---

Plan Title=Floodplain
Program Version=4.00
Geom File=g01
Flow File=f01
K Sum by GR=0
Std Step Tol=0.01
Critical Tol=0.01
Num of Std Step Trials=20
Max Error Tol=0.3
Flow Tol Ratio=0.001
Split Flow NTrial=30
Split Flow Tol=0.02
Split Flow Ratio=0.02
Log Output Level=0
Friction Slope Method=1
Unsteady Friction Slope Method=2
Unsteady Bridges Friction Slope Method=1
Global Log Level=0
CheckData=False
Run HTab=0
Run UNet=0
Run PostProcess=0
UNET Theta=0
UNET Theta Warmup=0
UNET ZTol=0
UNET ZSATol=0
UNET MxIter=0
UNET MaxInSteps=0
UNET DtIC=0
UNET DtMin=0
UNET MaxCRTS=0
UNET WFStab=0
UNET SFStab=0
UNET WFX=0
UNET SFX=0
UNET DSS MLevel=0
UNET DZMax Abort=0
UNET Convert EG Bridges=0
UNET Use Existing IB Tables=0
UNET Froude Limit=0
UNET Froude Power=0
Write IC File=0
Echo Input=False
Echo Output=False
Write Detailed=0

--- GRNBRIERCR.f01 (steady flow) ---

Flow Title=NFF Regression Equation
Program Version=4.00
Number of Profiles=1
Profile Names=P100yr
River Rch & RM=GRNBRIERCR,Main      ,15155
     363
River Rch & RM=GRNBRIERCR,Main      ,14951.1
     366
River Rch & RM=GRNBRIERCR,Main      ,12868.6
     405
River Rch & RM=GRNBRIERCR,Main      ,12562.3
     512
River Rch & RM=GRNBRIERCR,Main      ,10764.7
     552
River Rch & RM=GRNBRIERCR,Main      ,10475
     620
River Rch & RM=GRNBRIERCR,Main      ,9257.4
     672
River Rch & RM=GRNBRIERCR,Main      ,7779.7
     730
River Rch & RM=GRNBRIERCR,Main      ,6271.4
     794
River Rch & RM=GRNBRIERCR,Main      ,4774.8
     852
River Rch & RM=GRNBRIERCR,Main      ,281.8
     941
Boundary for River Rch & Prof#=GRNBRIERCR,Main      ,1
Up Type=0
Dn Type=3
Dn Slope=0.00434

--- GRNBRIERCR.g01 (geometry) ---

Geom Title=USGS 10m DEM
Program Version=4.00

River Reach=GRNBRIERCR      ,Main
Reach XY= 30
     1534607.721      415264.754     1535169.959      416103.745
     1535264.459      416437.996     1535076.494      416888.992
     1535190.234      417445.709     1535386.947      417779.459
     1535341.006      418136.262     1535481.807      418326.289
     1535414.843      418781.223     1535165.545      419174.683
     1535380.392      419622.184     1535373.395      419868.033
     1535512.476      420104.121     1535711.662      420113.584
      1535902.04      420299.206     1536356.343      420348.126
     1536762.486      421081.984      1536977.28      421067.272
     1537392.454      421449.211     1538330.263      421800.003
     1538224.094      422181.828     1538675.673      422626.083
     1538830.798      423468.239       1538769.9      424295.625
     1538884.128      424688.791     1538793.755      424845.138
     1538715.731      425536.898     1539229.311      426213.137
     1539519.603      426752.438     1539462.169      427240.018

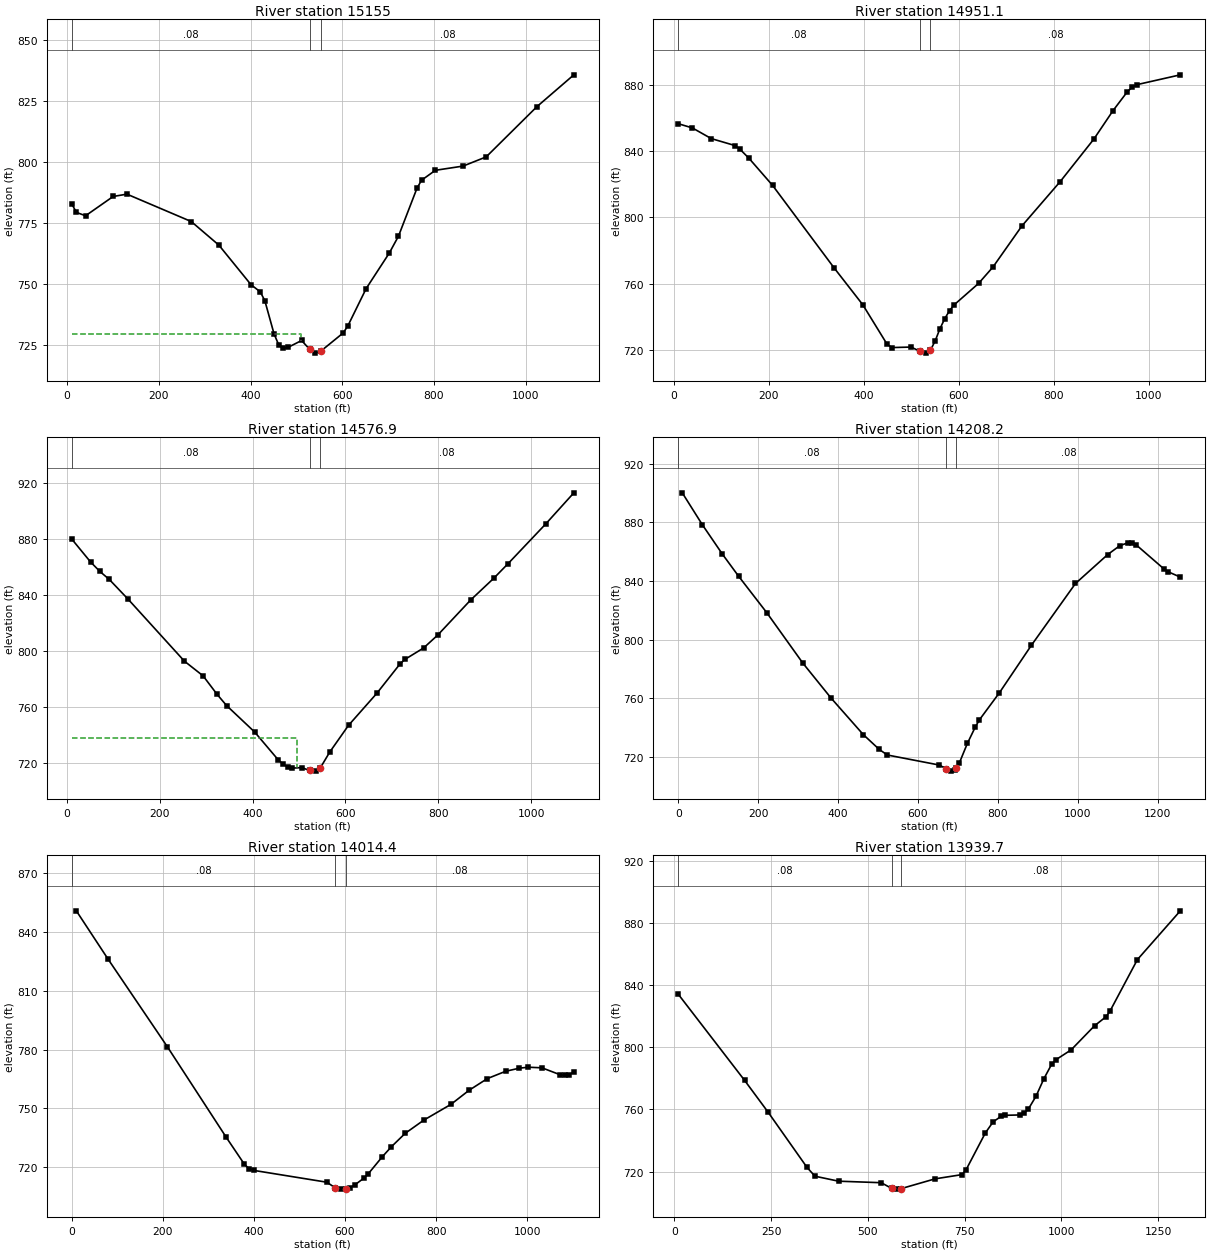
Type RM Length L Ch R = 1 ,15155   ,204.2,204,202.4
XS GIS Cut Line= 3
     1534129.043      415522.212     1534610.315      415274.208
     1535121.173      415035.943
#Sta/Elev= 30
      10  782.85    20.1  779.37    40.1  777.98   100.3  785.91   130.3  786.86
   270.7   775.6   330.9  765.91     401  749.65   421.1  746.74   431.1  743.09
   451.2  729.46   461.2  725.03   471.2  723.54   481.3  723.88   511.3  726.74
   528.9  723.11   541.4  721.55   553.9  722.47   601.8  729.81   611.9  732.64
   652.1  748.07   702.5  762.65   722.6   769.6   762.9  789.27   772.9  792.58
   803.1  796.66   863.5  798.39   913.9  802.17  1024.6  822.81  1105.1  835.88
#Mann= 3 , 0 , 0
      10     .08       0   528.9    .045       0   553.9     .08       0
#XS Ineff= 2 , 0
          509.73  729.29
Permanent Ineff=
       F       F
Bank Sta=528.9,553.9
XS Rating Curve= 0 ,0
Exp/Cntr=0.3,0.1

Type RM Length L Ch R = 1 ,14951.1 ,376.8,374.2,371.2
XS GIS Cut Line= 4
     1534247.362      415697.119     1534550.876      415527.356
     1534859.534      415373.027     1535178.481      415177.544
#Sta/Elev= 30
     9.9  856.71    39.7  854.15    79.5   847.7   129.2  843.51   139.1  841.49
     159  835.73   208.7  819.34   337.8  769.59   398.5  747.18   449.3  723.45
   459.4  721.31     500  721.62     518  719.17   530.5  717.95   540.6  719.56
   550.8  725.34   560.9  732.75   571.1  738.84   581.2  743.73   591.4  747.31
   642.1  760.09   672.6  770.06   733.3  794.84   814.2  821.75     885  847.45
   925.4  864.68   955.7  876.16   965.8  878.82   975.9  880.35  1066.9  886.27
#Mann= 3 , 0 , 0
     9.9     .08       0     518    .045       0   540.6     .08       0
Bank Sta=518,540.6
XS Rating Curve= 0 ,0
Exp/Cntr=0.3,0.1

Type RM Length L Ch R = 1 ,14576.9 ,374.2,368.7,363.6
XS GIS Cut Line= 3
     1534448.481      416051.517     1534911.985      415763.044
     1535366.466      415459.853
#Sta/Elev= 30
    10.1  880.17    50.6   863.8    70.8  856.99      91  851.28   131.4  837.21
   252.8  792.85   293.2  782.29   323.5     769   343.7  761.09   404.4  742.09
     455  722.24   465.1  719.21   475.2   717.2   485.3  716.26   505.5  716.67
   523.3  714.59   535.8  714.14   545.9  716.51   566.2   727.8   606.6  746.89
   667.3  769.69   717.9  790.95   728.1  794.07   768.5  802.27   798.9  811.49
   869.7  836.53   920.3  852.33   950.6  862.62  1031.6  890.97  1092.3  913.27
#Mann= 3 , 0 , 0
    10.1     .08       0   523.3    .045       0   545.9     .08       0
#XS Ineff= 2 , 0
          495.37  738.19
Permanent Ineff=
       F       F
Bank Sta=523.3,545.9
XS Rating Curve= 0 ,0
Exp/Cntr=0.3,0.1

Type RM Length L Ch R = 1 ,14208.2 ,184.4,193.8,203.2
XS GIS Cut Line= 4
     1534514.866      416309.291     1534967.565      416211.549
     1535353.388      415846.303     1535615.747      415846.303
#Sta/Elev= 30
    10.1  900.21    60.4  878.42   110.7  858.32     151  843.34   221.5  818.47
   312.1  783.95   382.6  760.14   463.1  735.26   503.2  725.11   523.3  721.31
   653.6  714.45   671.2  711.83   683.7   710.3   693.7  711.24   696.2   712.4
   703.7   715.9   723.8  729.24   743.8   740.5   753.8  745.27     804  763.79
   884.1   796.2   994.4  838.35  1075.1   858.1  1105.4  864.16  1125.6  866.09
  1135.7  866.19  1145.8  864.82  1216.4  848.15  1226.5  846.32  1256.8  842.69
#Mann= 3 , 0 , 0
       0     .08       0   671.2    .045       0   696.2     .08       0
Bank Sta=671.2,696.2
XS Rating Curve= 0 ,0
Exp/Cntr=0.3,0.1

Type RM Length L Ch R = 1 ,14014.4 ,68.5,74.7,81
XS GIS Cut Line= 4
     1534661.987      416422.047     1535107.981      416276.901
     1535385.078      416152.867     1535707.039      416081.613
#Sta/Elev= 30
      10  850.68    79.8  826.03   209.6  781.52   339.3  735.23   379.2  721.49
   389.2   719.3   399.2  718.44   560.1   712.4     578  709.62   590.5  708.88
     603   709.1   610.7  709.52   620.8  710.92   641.1  714.42   651.2  716.74
   681.5  725.29   701.8  730.48   732.1   737.3   772.6  743.98   832.6  752.08
   872.5  759.27   912.5   765.2   952.5  768.91   982.5   770.5  1002.4     771
  1032.4  770.69  1072.4  767.15  1082.4  766.85  1092.4  767.25  1102.4  768.52
#Mann= 3 , 0 , 0
       0     .08       0     578    .045       0     603     .08       0
Bank Sta=578,603
XS Rating Curve= 0 ,0
Exp/Cntr=0.3,0.1

Type RM Length L Ch R = 1 ,13939.7 ,186.2,205.8,225.3
XS GIS Cut Line= 5
     1534704.349      416492.295     1534997.615      416384.477
     1535135.622      416319.786     1535398.699      416268.033
     1535894.664      416556.986
#Sta/Elev= 30
    10.1  834.08   181.4  778.68   241.9   758.3   342.9   722.6   363.3  716.99
   424.2  713.79   534.4  712.81   561.6  709.13   573.9  708.68   586.6  709.06
   673.4  715.29   743.1  718.02   753.1  720.89   803.5  744.87   823.6  751.99
   843.8  755.45   853.8  756.16   894.1  756.41   904.2  757.64   914.3  760.12
   934.4   768.5   954.5  779.65   974.7  789.03   984.7  791.76    1025  798.27
  1085.4  813.76  1115.7  819.69  1125.7  823.36  1196.2  856.35    1307  887.71
#Mann= 3 , 0 , 0
    10.1     .08       0   561.6    .045       0   586.6     .08       0
Bank Sta=561.6,586.6
XS Rating Curve= 0 ,0
Exp/Cntr=0.3,0.1

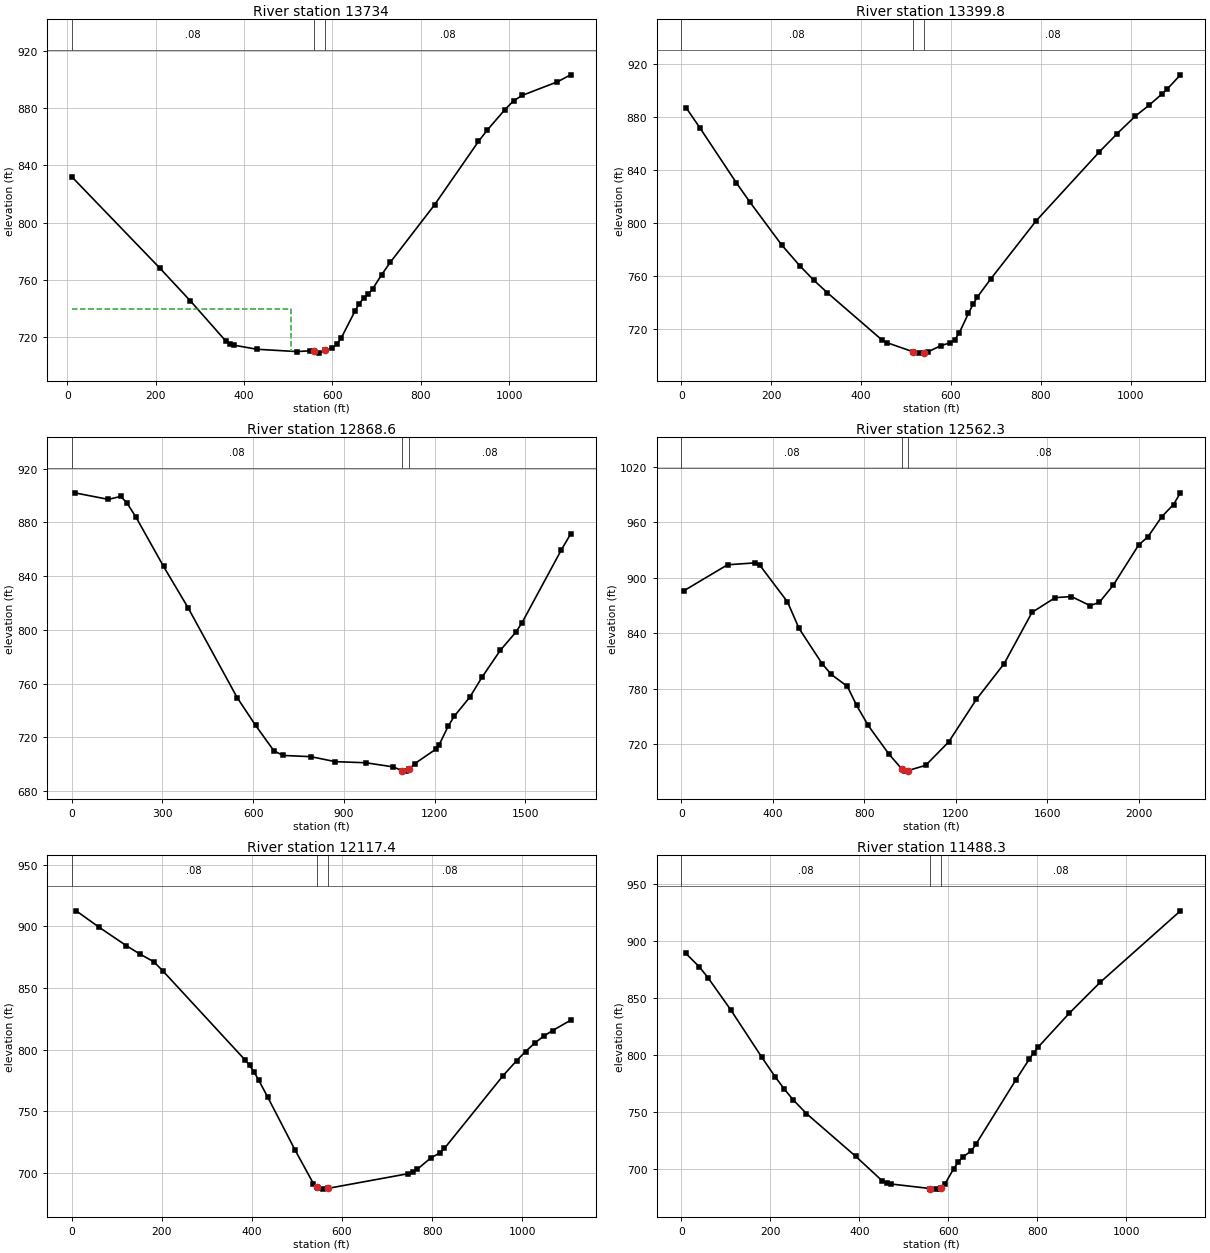
Type RM Length L Ch R = 1 ,13734   ,340.7,334.1,327.1
XS GIS Cut Line= 4
     1534704.349      416518.172     1535053.681      416401.728
     1535411.637      416587.175     1535717.841      416789.874
#Sta/Elev= 30
      10  832.21     209   768.3   278.7  745.13   358.3  717.22   368.2   715.1
   378.3  714.12   428.7  711.32   519.4  709.69   549.6  710.25   557.3  709.83
  569.67   708.6   582.3  710.45     600  712.54   610.1  714.78   620.2  719.43
   650.4  737.76   660.5   743.3   670.6  747.16   680.7  749.87   690.7  753.51
   710.9  763.36   731.1  772.33   830.9  812.48   930.2  856.86     950  864.78
   989.7  879.01  1009.6  885.31  1029.4  889.12  1108.8  898.59  1138.6  903.48
#Mann= 3 , 0 , 0
      10     .08       0   557.3    .045       0   582.3     .08       0
#XS Ineff= 2 , 0
          506.34  739.38
Permanent Ineff=
       F       F
Bank Sta=557.3,582.3
XS Rating Curve= 0 ,0
Exp/Cntr=0.3,0.1

Type RM Length L Ch R = 1 ,13399.8 ,520.6,531.2,512.1
XS GIS Cut Line= 3
     1534580.688      416672.348     1535103.636      416800.693
     1535662.447      416925.538
#Sta/Elev= 30
    10.2  887.28    40.6  872.26   121.9  830.67   152.4  815.95   223.5  783.44
   264.2  767.59   294.6  756.99   325.1  747.42     447  711.66   457.2  709.82
   515.8   702.9   528.3  701.88   540.8  702.11   548.5  702.83   578.6  707.64
   598.7  709.71   608.8  712.01   618.8  717.37   638.9  731.84     649  738.63
     659  744.33   689.1  758.11   789.6  801.73   930.2  853.76   970.4  867.73
  1010.6  880.87  1040.7  888.96  1070.9  897.88  1080.9  901.07  1111.1  912.06
#Mann= 3 , 0 , 0
       0     .08       0   515.8    .045       0   540.8     .08       0
Bank Sta=515.8,540.8
XS Rating Curve= 0 ,0
Exp/Cntr=0.3,0.1

Type RM Length L Ch R = 1 ,12868.6 ,324.5,306.3,288.1
XS GIS Cut Line= 3
     1534172.634      416820.106     1535036.728      417266.533
     1535703.347       417150.97
#Sta/Elev= 30
    10.1  901.91   121.6  897.04   162.1  899.24   182.4  894.55   212.8  883.77
   303.9  847.15     385   816.4   547.1  749.65   607.9     729   668.7     710
   699.1   706.6   790.2  705.72   871.3     702   972.6  701.17  1063.5  698.07
  1091.4  695.32  1103.9  694.95  1116.4  696.62  1134.2  700.55  1204.9  711.44
    1215  714.65  1245.2   728.7  1265.4  735.99  1315.9  749.91  1356.3  764.77
  1416.9  784.83  1467.4  798.07  1487.6  804.93  1618.9  859.62  1649.2  871.26
#Mann= 3 , 0 , 0
       0     .08       0  1091.4    .045       0  1116.4     .08       0
Bank Sta=1091.4,1116.4
XS Rating Curve= 0 ,0
Exp/Cntr=0.3,0.1

Type RM Length L Ch R = 1 ,12562.3 ,421.9,444.9,467.9
XS GIS Cut Line= 4
     1534404.579      417923.134     1535193.193      417588.102
     1535445.755      417314.922     1536352.918      417021.125
#Sta/Elev= 30
    10.1     886   201.6  914.17   322.6  916.23   342.7  913.69   463.7  874.02
   514.1  845.36   614.9  807.21   655.2  795.53   725.8  782.45   766.1  762.03
   816.5  740.37   907.1  709.37     965  692.83   977.5  690.87     990  691.41
    1068  697.13  1168.5  722.38  1289.7  768.48  1411.5  807.25  1533.2  862.67
  1634.6   878.6  1705.6  879.77  1786.8  869.99  1827.4  873.45  1888.2  891.96
  1999.8  935.67  2040.4  944.51  2101.3  966.36    2152  979.38  2182.4  992.02
#Mann= 3 , 0 , 0
       0     .08       0     965    .045       0     990     .08       0
Bank Sta=965,990
XS Rating Curve= 0 ,0
Exp/Cntr=0.3,0.1

Type RM Length L Ch R = 1 ,12117.4 ,628.8,629,629.3
XS GIS Cut Line= 3
     1534812.061      417911.298     1535389.057       417917.98
     1535919.428      417918.351
#Sta/Elev= 30
    10.1  912.58    60.7  899.33   121.5  884.28   151.9  877.43   182.2  871.29
   202.5  863.81   384.7   791.6   394.8  787.26   404.9  781.73   415.1  775.16
   435.3  761.26     496  718.29   536.5  691.19   544.3  688.26   546.7  687.35
   556.8  686.65   569.3   687.3   747.2  699.21   757.2  700.47   767.2  702.82
   797.2     712   817.2  716.06   827.2  719.67   957.3  778.69   987.3  790.84
  1007.3  798.34  1027.3  805.08  1047.4  810.78  1067.4  815.39  1107.4  823.74
#Mann= 3 , 0 , 0
       0     .08       0   544.3    .045       0   569.3     .08       0
Bank Sta=544.3,569.3
XS Rating Curve= 0 ,0
Exp/Cntr=0.3,0.1

Type RM Length L Ch R = 1 ,11488.3 ,385.6,400.5,415.4
XS GIS Cut Line= 3
     1534897.921      418489.183     1535419.984      418495.265
     1536019.681      418504.071
#Sta/Elev= 30
      10  889.08    40.2  877.35    60.2  867.53   110.4  839.87   180.7  798.02
   210.8  780.84   230.9   770.3     251  760.78   281.1  748.61   391.6   711.2
   451.8  689.51   461.9  687.62   471.9  686.86   559.6  682.88   572.1  682.39
   582.1  682.63   584.6  683.66   592.1  686.76   612.1  700.31   622.1  706.02
   632.1  710.43     652  716.04     662  721.77     752  778.32     782   796.4
     792   802.1     802  806.97     872  836.72   941.9  863.96  1121.9  926.49
#Mann= 3 , 0 , 0
       0     .08       0   559.6    .045       0   584.6     .08       0
Bank Sta=559.6,584.6
XS Rating Curve= 0 ,0
Exp/Cntr=0.3,0.1

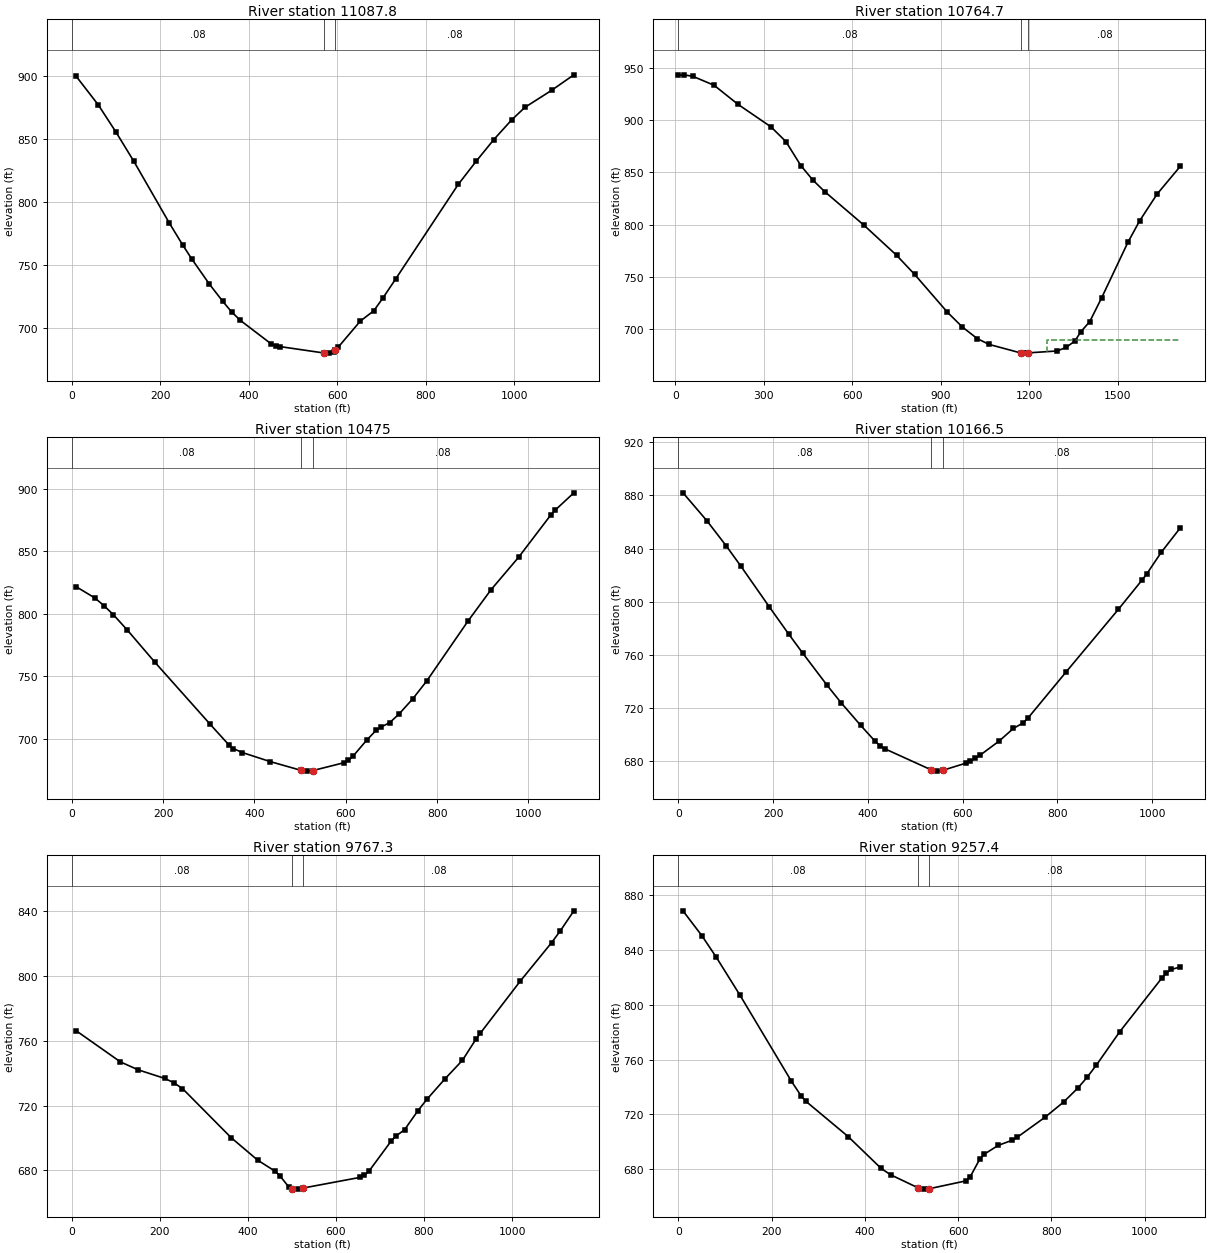
Type RM Length L Ch R = 1 ,11087.8 ,336.5,323.1,309.7
XS GIS Cut Line= 3
     1534853.006      418624.124     1535244.736      418804.525
     1535843.295      419174.519
#Sta/Elev= 30
      10  900.06    60.2  877.26   100.3  855.58   140.4  832.54   220.7  783.52
   250.7  766.26   270.8  755.37   310.9  735.26     341  721.62   361.1  713.19
   381.1  706.38   451.4  687.57   461.4  686.16   471.5  685.54   569.6  680.53
   582.1   680.4   592.1  681.69   594.6  682.53   602.2  685.07   652.4  705.86
   682.6  713.95   702.7  723.79   732.9  739.61   873.6  814.26   913.8  832.47
     954  849.83   994.2  865.39  1024.4  875.42  1084.7  888.92    1135  901.23
#Mann= 3 , 0 , 0
       0     .08       0   569.6    .045       0   594.6     .08       0
Bank Sta=569.6,594.6
XS Rating Curve= 0 ,0
Exp/Cntr=0.3,0.1

Type RM Length L Ch R = 1 ,10764.7 ,302.5,289.7,277
XS GIS Cut Line= 4
     1534105.628      418680.821     1535028.254      419124.094
      1535486.99      419170.483     1535713.781      419170.483
#Sta/Elev= 30
    10.1     943    30.4  943.45    60.8  941.89   131.7  933.42   212.8  915.14
   324.3  893.63     375  879.49   425.6  856.52   466.2  842.67   506.7  831.53
   638.5  799.66     750  770.63   810.8  752.39   922.2  716.09   972.9  701.91
  1023.6  690.75  1063.7  685.22  1171.5  677.01    1184  676.89  1196.5  677.14
  1294.2  678.96  1324.3  682.33  1354.4  688.53  1374.4  697.35  1404.5  707.04
  1444.6  729.67    1534  783.08  1573.4  803.46  1632.6  829.15  1711.5  855.87
#Mann= 3 , 0 , 0
    10.1     .08       0  1171.5    .045       0  1196.5     .08       0
#XS Ineff= 2 , 0
                         1259.06          689.54
Permanent Ineff=
       F       F
Bank Sta=1171.5,1196.5
XS Rating Curve= 0 ,0
Exp/Cntr=0.3,0.1

Type RM Length L Ch R = 1 ,10475   ,304.3,308.5,312.7
XS GIS Cut Line= 3
     1534805.974      419581.404     1535308.326      419369.415
     1535839.462      419211.164
#Sta/Elev= 30
    10.1  821.42    50.5  812.54    70.7  806.32    90.9  799.22   121.2  787.06
   181.7  761.25   302.9  711.59   343.3  695.32   353.4  692.14   373.6   688.9
   434.2  681.72   502.5  674.63     515  674.05   527.5  674.46   595.6  680.72
   605.7  682.58   615.8  685.93     646  698.88   666.2  706.55   676.2  709.09
   696.4  712.86   716.6  719.67   746.8   731.9     777  745.97   867.7  794.05
   918.1   819.1   978.5  845.06  1049.1  878.93  1059.2  882.96  1099.5   896.6
#Mann= 3 , 0 , 0
       0     .08       0   502.5    .045       0   527.5     .08       0
Bank Sta=502.5,527.5
XS Rating Curve= 0 ,0
Exp/Cntr=0.3,0.1

Type RM Length L Ch R = 1 ,10166.5 ,407.4,399.1,392.1
XS GIS Cut Line= 3
     1534859.607      419804.475     1535290.881      419692.344
     1535886.038      419541.398
#Sta/Elev= 30
    10.1  881.95    60.8   860.8   101.3  842.04   131.7  827.04   192.4  796.09
   232.9  775.81   263.3   761.1     314  737.27   344.3  723.81   384.8  707.13
   415.2  695.17   425.4  691.87   435.5   689.5   533.8  673.59   546.3  672.62
   558.8  673.28   606.7  678.58   616.7  680.11   626.8  682.18   636.9  684.58
   677.1  695.19   707.3  704.72   727.4  708.82   737.5  712.27     818  746.97
   928.8  794.28   979.1  816.44   989.2  821.18  1019.4  837.22  1059.6  855.61
#Mann= 3 , 0 , 0
       0     .08       0   533.8    .045       0   558.8     .08       0
Bank Sta=533.8,558.8
XS Rating Curve= 0 ,0
Exp/Cntr=0.3,0.1

Type RM Length L Ch R = 1 ,9767.3  ,525.6,509.9,492.9
XS GIS Cut Line= 3
     1535033.408       420283.82     1535465.322      420026.556
     1536028.195      419727.152
#Sta/Elev= 30
    10.1  766.16   110.6  746.93   150.8  742.05   211.1  736.75   231.3  734.14
   251.4  730.51     362  700.17   422.3  686.28   462.5  679.35   472.6  676.65
   492.7  669.82   500.3  668.76   512.8  668.41   525.3  669.07   654.5  675.65
   664.6  676.86   674.8  679.43   725.4  698.08   735.5  701.05   755.7  705.02
   786.1   716.8   806.3  723.77   846.8  736.23   887.3  747.93   917.6  760.82
   927.8  764.63  1018.8  796.87  1089.7  820.53  1109.9  827.96  1140.3   840.2
#Mann= 3 , 0 , 0
       0     .08       0   500.3    .045       0   525.3     .08       0
Bank Sta=500.3,525.3
XS Rating Curve= 0 ,0
Exp/Cntr=0.3,0.1

Type RM Length L Ch R = 1 ,9257.4  ,673,690.1,706.8
XS GIS Cut Line= 3
     1535621.003      420727.093     1535865.673      420238.717
     1536110.665      419768.386
#Sta/Elev= 30
    10.1  868.78    50.6  850.64    80.9  835.21   131.5  807.59   242.8  744.11
     263   733.7   273.1  729.67   364.2  703.74     435  680.44   455.2   675.8
   513.5  666.33     526  665.27   538.5  665.59   616.3  671.27   626.3  674.47
   646.3  687.08   656.3  690.86   686.3  697.29   716.3  701.05   726.3  703.07
   786.4  717.83   826.4  728.99   856.4  739.04   876.4  746.93   896.4   755.9
   946.5   780.3  1036.5  819.44  1046.5  823.23  1056.5  825.88  1076.5   827.7
#Mann= 3 , 0 , 0
       0     .08       0   513.5    .045       0   538.5     .08       0
Bank Sta=513.5,538.5
XS Rating Curve= 0 ,0
Exp/Cntr=0.3,0.1

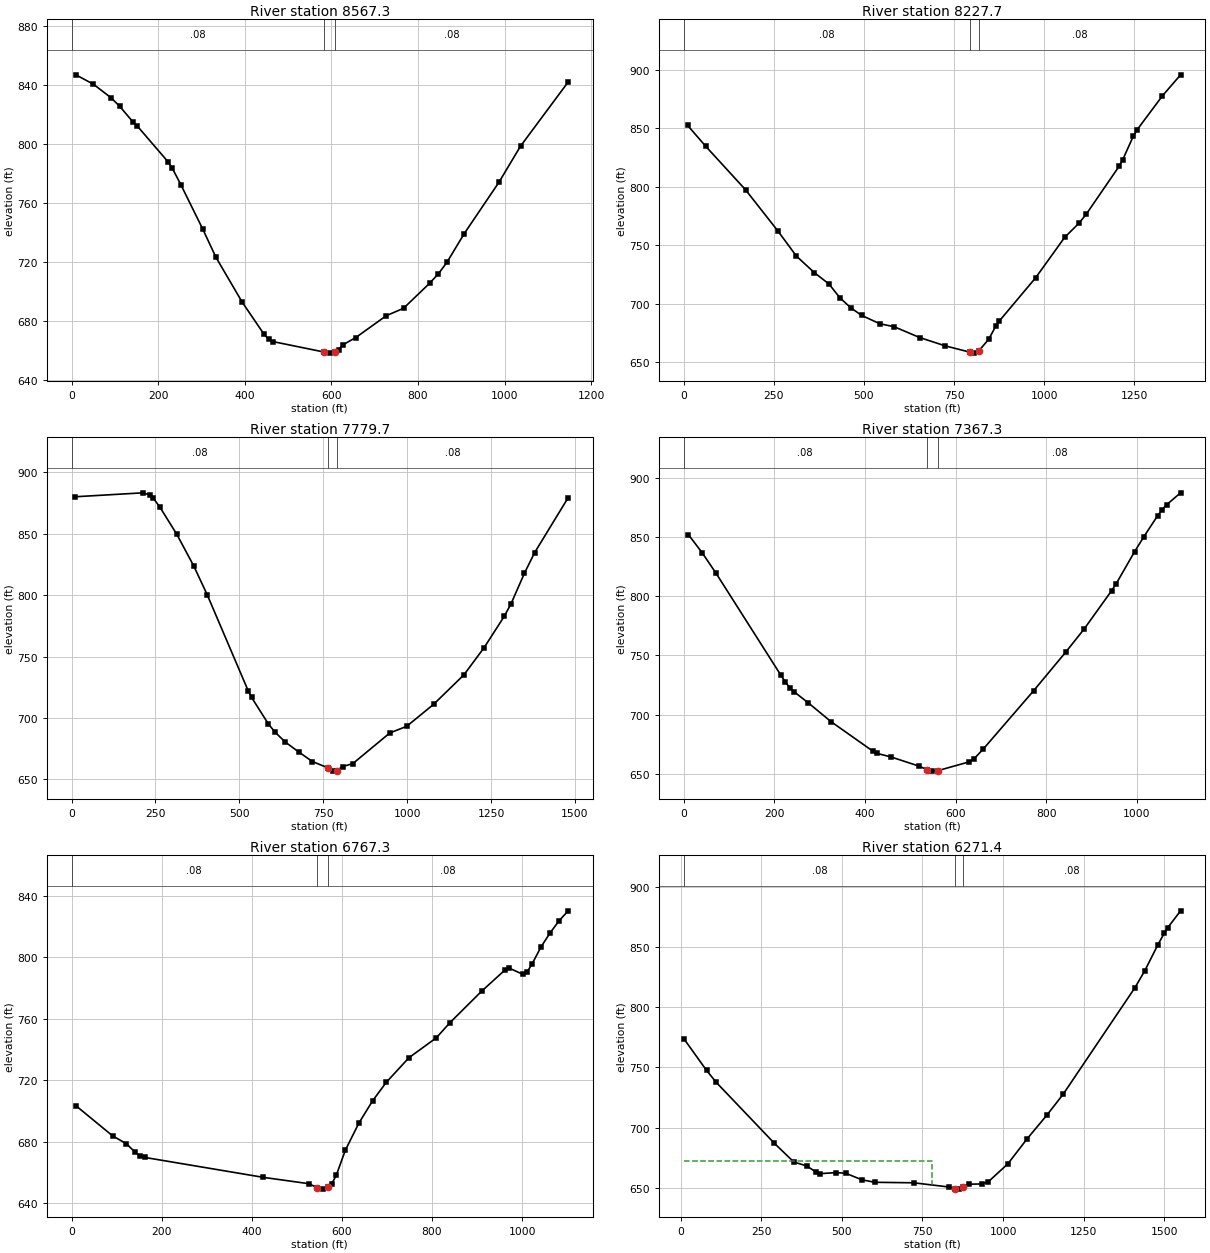
Type RM Length L Ch R = 1 ,8567.3  ,340.6,339.7,338.9
XS GIS Cut Line= 3
     1535904.491      420768.328     1536437.523      420478.768
     1536911.131      420218.605
#Sta/Elev= 30
    10.1   847.2    50.6  840.82      91  831.72   111.2  825.88   141.5   815.4
   151.7  812.54   222.4  788.38   232.5  783.98   252.8  772.51   303.3  742.42
   333.6  723.41   394.3  692.93   444.8  671.14     455  667.84   465.1  666.26
     584  659.12   596.5  658.43     609  659.22   616.6  660.88   626.6  664.04
   656.6  669.03   726.7  683.79   766.7  688.83   826.8  705.78   846.8  712.09
   866.8  719.93   906.8  739.45   986.9  774.27  1036.9  798.83    1147  842.37
#Mann= 3 , 0 , 0
       0     .08       0     584    .045       0     609     .08       0
Bank Sta=584,609
XS Rating Curve= 0 ,0
Exp/Cntr=0.3,0.1

Type RM Length L Ch R = 1 ,8227.7  ,483.5,448,412.4
XS GIS Cut Line= 3
     1535919.954       421175.52     1536693.105      420721.939
     1537110.606      420479.685
#Sta/Elev= 30
    10.1  852.59    60.4  834.72   171.2  797.47   261.9   761.9   312.2  740.81
   362.6  726.53   402.9   716.9   433.1  705.13   463.3  696.58   493.5  690.05
   543.9  682.95   584.2  680.33   654.7  671.13   725.2  664.05   793.2   658.7
   805.7   657.8   818.2   659.5     846   669.5   866.2  680.93   876.2  685.39
   976.8  722.28  1057.3  756.78  1097.5  769.03  1117.6  776.76  1208.1  817.39
  1218.2  822.97  1248.3  843.59  1258.4  848.74  1328.8  877.81  1379.1  895.73
#Mann= 3 , 0 , 0
       0     .08       0   793.2    .045       0   818.2     .08       0
Bank Sta=793.2,818.2
XS Rating Curve= 0 ,0
Exp/Cntr=0.3,0.1

Type RM Length L Ch R = 1 ,7779.7  ,386.3,412.4,441.2
XS GIS Cut Line= 4
     1536528.673      421747.145     1536889.476      421221.402
     1536801.852      420870.908      1537131.73      420520.413
#Sta/Elev= 30
    10.1  880.13   212.5  883.35   232.8  881.68   242.9  879.28   263.2  871.81
   313.8  849.56   364.4  823.75   404.9  800.06   526.3  722.31   536.4  716.89
     587  695.02   607.3  688.26   637.6  680.32   677.8   672.2   717.9  664.57
   765.6  659.25   778.1  656.75   790.6  657.25   808.2  660.47   838.4   662.9
   948.7  687.85   998.9  693.23  1079.1  711.15  1169.4  735.15  1229.6   757.3
  1289.7  782.85  1309.8  793.02  1349.9  817.99    1380  834.62  1480.2  879.48
#Mann= 3 , 0 , 0
       0     .08       0   765.6    .045       0   790.6     .08       0
Bank Sta=765.6,790.6
XS Rating Curve= 0 ,0
Exp/Cntr=0.3,0.1

Type RM Length L Ch R = 1 ,7367.3  ,605.9,600,590.1
XS GIS Cut Line= 3
     1536835.675      421681.093     1537185.985      421259.056
     1537575.993      420874.299
#Sta/Elev= 30
    10.2  851.77    40.6  836.45    71.1  819.24   213.3  733.77   223.5  727.84
   233.6  722.78   243.8  719.16   274.2  710.14     325  694.09   416.4  669.47
   426.6  667.36   457.1  664.39     518  656.77     536   653.8   548.5  652.43
     561  652.87   629.6  660.25   639.8  662.61   660.1  670.74   771.7  720.11
   842.7  752.72   883.3  772.19   944.2  804.65   954.3  810.52   994.9  837.56
  1015.2  850.06  1045.6  867.77  1055.8  872.96  1065.9  877.19  1096.3  887.09
#Mann= 3 , 0 , 0
       0     .08       0     536    .045       0     561     .08       0
Bank Sta=536,561
XS Rating Curve= 0 ,0
Exp/Cntr=0.3,0.1

Type RM Length L Ch R = 1 ,6767.3  ,499.5,496,493.8
XS GIS Cut Line= 3
     1537435.329      422036.294     1537693.368      421542.529
     1537923.621      421048.513
#Sta/Elev= 30
    10.1  703.36    91.2   683.8   121.6  678.72   141.8  672.97   151.9  670.87
   162.1  669.78   425.4  656.79   526.7  652.64   544.6  650.14   557.1  649.11
   569.6  650.46   577.3  652.54   587.4  657.99   607.6  674.42   637.9  692.23
   668.2  706.64   698.4  718.64   748.9  734.72   809.5  747.64   839.7  757.49
   910.4  778.09   960.9  791.55     971  793.06  1001.2  789.04  1011.3  790.74
  1021.4  795.39  1041.6  806.71  1061.8   815.9    1082  823.89  1102.2  830.34
#Mann= 3 , 0 , 0
       0     .08       0   544.6    .045       0   569.6     .08       0
Bank Sta=544.6,569.6
XS Rating Curve= 0 ,0
Exp/Cntr=0.3,0.1

Type RM Length L Ch R = 1 ,6271.4  ,751,765.6,779.3
XS GIS Cut Line= 4
     1537492.027      422263.085     1538038.386      422010.523
     1538203.325       421567.25     1538167.245      421093.051
#Sta/Elev= 30
      10  773.89    80.3   747.6   110.4  737.65   290.9  686.95   351.1  671.44
   391.2   668.2   421.3  662.84   431.4  661.78   481.5  662.67   511.6  662.15
   561.8  656.72   601.9  654.62   722.7   654.2   833.4  650.67   851.1  649.25
   863.6  648.94   876.1  650.89   893.7  653.01     934  653.26   954.1  655.05
  1014.5  669.89  1074.9  690.87  1135.6  710.36  1186.2  727.78  1408.8   816.3
  1439.1  830.24  1479.6  851.75  1499.9  861.68    1510  865.99  1550.4  880.17
#Mann= 3 , 0 , 0
      10     .08       0   851.1    .045       0   876.1     .08       0
#XS Ineff= 2 , 0
          778.31  672.52
Permanent Ineff=
       F       F
Bank Sta=851.1,876.1
XS Rating Curve= 0 ,0
Exp/Cntr=0.3,0.1

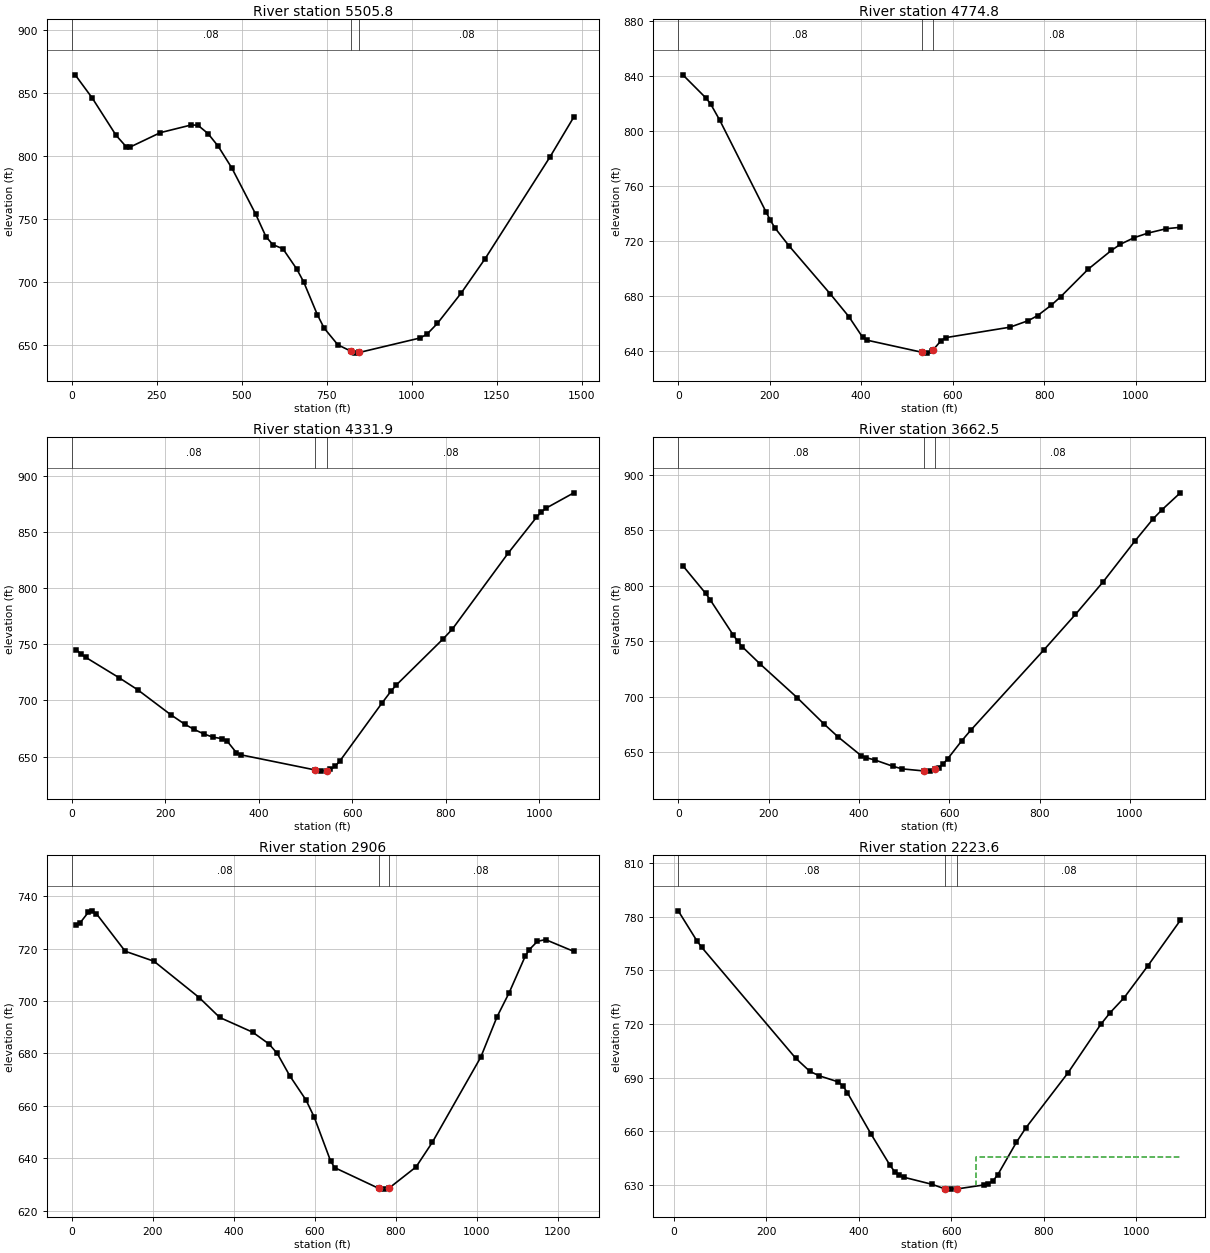
Type RM Length L Ch R = 1 ,5505.8  ,717.4,730.9,744.4
XS GIS Cut Line= 4
     1537878.602      422974.384     1538172.399      422438.333
      1538517.74      422098.147     1538888.911      422010.963
#Sta/Elev= 30
      10   864.4    60.1  846.03   130.3  816.38   160.3  807.28   170.4   806.9
   260.5  818.49   350.7  824.54   370.8  824.45   400.8  817.79   430.9  807.68
     471  790.42   541.1  753.84   571.2  736.02   591.2  729.69   621.4  726.25
   661.8   710.3     682  700.21   722.4  674.11   742.6   663.3     783  650.05
     821  645.06   833.5  643.47     846  643.99  1025.3  655.52  1045.5  658.58
  1075.8  667.06  1146.2   691.3  1216.4  718.51  1407.1   799.2  1477.3  830.95
#Mann= 3 , 0 , 0
       0     .08       0     821    .045       0     846     .08       0
Bank Sta=821,846
XS Rating Curve= 0 ,0
Exp/Cntr=0.3,0.1

Type RM Length L Ch R = 1 ,4774.8  ,438.3,442.9,447.6
XS GIS Cut Line= 3
     1538177.554       423005.31     1538718.989      422845.925
     1539229.038      422690.895
#Sta/Elev= 30
    10.1  840.61    60.5  823.77    70.6  819.55    90.7  807.63   191.5  741.17
   201.6  734.67   211.7  729.11   241.9  716.32   332.6  681.13   372.9  664.76
   403.1   649.7   413.2  647.56   531.8  638.88   544.3  638.18   554.3  639.46
   556.8  640.41   574.5  647.26   584.5  649.43   725.3  657.06   765.6  661.86
   785.7  665.52   815.9  673.18     836  679.21   896.3   699.3   946.6  712.84
   966.7  717.38   996.9  722.21  1027.1  725.52  1067.3  728.72  1097.5  729.68
#Mann= 3 , 0 , 0
       0     .08       0   531.8    .045       0   556.8     .08       0
Bank Sta=531.8,556.8
XS Rating Curve= 0 ,0
Exp/Cntr=0.3,0.1

Type RM Length L Ch R = 1 ,4331.9  ,668.4,669.4,670.8
XS GIS Cut Line= 3
     1538257.915      423316.333     1538770.302      423283.644
     1539326.971      423216.638
#Sta/Elev= 30
    10.1  745.06    20.1  741.12    30.2  738.27   100.7  720.34   140.9  709.53
   211.4   687.4   241.6  678.84   261.7  674.19   281.9   670.3     302  667.25
   322.2  665.97   332.2  663.84   352.4  653.38   362.4  651.51     521  638.06
   533.5  637.05     546  637.52   553.5  638.55   563.5  641.42   573.5  646.03
   663.6  697.65   683.6   708.6   693.6  713.43   793.8  754.51   813.8  763.28
   933.9   831.3     994  862.95    1004  867.56    1014  871.03  1074.1  884.84
#Mann= 3 , 0 , 0
       0     .08       0     521    .045       0     546     .08       0
Bank Sta=521,546
XS Rating Curve= 0 ,0
Exp/Cntr=0.3,0.1

Type RM Length L Ch R = 1 ,3662.5  ,756.1,756.5,756.5
XS GIS Cut Line= 3
     1538259.282      423967.372     1538825.284      423940.662
     1539370.057      423924.734
#Sta/Elev= 30
    10.1  818.02    60.7   793.1    70.8  787.28   121.4  755.88   131.5  750.15
   141.7  745.09   182.1  729.27   263.1  699.38   323.8  675.22   354.1  663.92
   404.7  647.25   414.9   645.4   435.1  643.29   475.6  637.54   495.8  635.24
     544  633.37   556.5  633.22     569  634.69   576.7  636.36   586.8  639.88
   596.9  644.48   627.2  660.27   647.4  669.92   808.9  741.94   879.5   774.2
   940.1  803.16  1010.7  839.96  1051.1  860.01  1071.3  868.41  1111.6  883.53
#Mann= 3 , 0 , 0
       0     .08       0     544    .045       0     569     .08       0
Bank Sta=544,569
XS Rating Curve= 0 ,0
Exp/Cntr=0.3,0.1

Type RM Length L Ch R = 1 ,2906    ,677.3,682.4,687.6
XS GIS Cut Line= 3
     1538109.666      424714.342     1538809.001      424680.742
     1539346.707      424637.027
#Sta/Elev= 30
    10.1  729.03    20.3  729.77    40.6   733.8    50.7  734.41    60.9   733.3
   131.9  718.99   202.9  715.18   314.6  701.31   365.3  693.72   446.5  688.12
   487.1  683.59   507.3  680.01   537.8  671.58   578.4   662.2   598.7  655.67
   639.3  638.85   649.4   636.4   757.6  628.54   770.1  628.23   782.6  628.52
     850  636.69     890  646.04  1009.8  678.57  1049.8  693.93  1079.8  703.14
  1119.7  717.15  1129.7  719.61  1149.7  722.77  1169.7  723.43  1239.6  718.92
#Mann= 3 , 0 , 0
       0     .08       0   757.6    .045       0   782.6     .08       0
Bank Sta=757.6,782.6
XS Rating Curve= 0 ,0
Exp/Cntr=0.3,0.1

Type RM Length L Ch R = 1 ,2223.6  ,411,392.3,373.6
XS GIS Cut Line= 3
     1538153.568       425262.44     1538699.431      425319.209
     1539242.749      425378.307
#Sta/Elev= 30
    10.2  783.43    50.8   766.5      61  762.96   264.2  700.77   294.7  693.44
   315.1  690.94   355.7  687.58   365.9  685.39     376  681.38   426.8  658.33
   467.5  640.97   477.7  637.26   487.8   635.1     498  634.08   558.9  630.11
   586.9  627.55   599.4  627.43   611.9  627.51   670.3  629.75   680.4  630.43
   690.5  632.11   700.6  635.42   741.1   653.7   761.3   661.7   852.4  692.55
   923.3  719.74   943.5  726.31   973.9  734.73  1024.5  752.37  1095.3  778.08
#Mann= 3 , 0 , 0
    10.2     .08       0   586.9    .045       0   611.9     .08       0
#XS Ineff= 2 , 0
                          653.79          645.66
Permanent Ineff=
       F       F
Bank Sta=586.9,611.9
XS Rating Curve= 0 ,0
Exp/Cntr=0.3,0.1

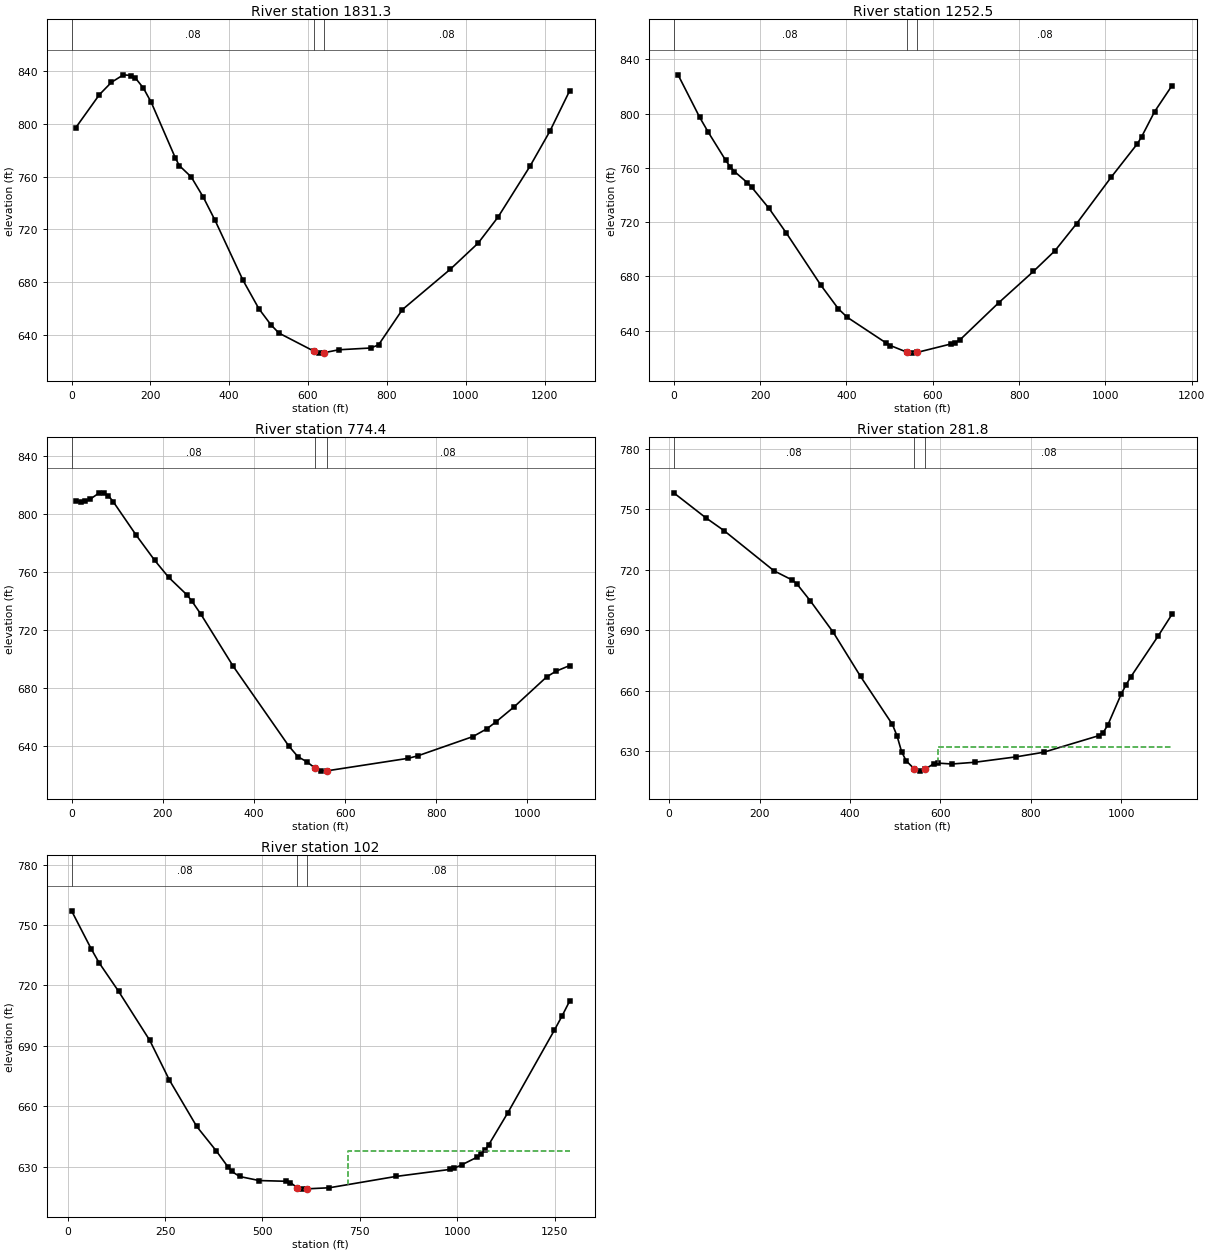
Type RM Length L Ch R = 1 ,1831.3  ,583.5,578.7,574.1
XS GIS Cut Line= 3
      1538252.82      426016.469     1538713.605      425742.263
     1539326.971      425350.533
#Sta/Elev= 30
    10.1  796.77    70.8  822.06   101.2  831.34   131.5  836.98   151.8  836.43
   161.9  834.59   182.1  827.03   202.3  816.06     263  774.32   273.2  768.35
   303.5  759.75   333.9   744.6   364.2   726.8     435  681.53   475.5  659.91
   505.8  647.87   526.1  641.62   614.7  627.95   627.2  626.44   639.7  626.68
   677.7  628.97   758.6  630.31   778.8  632.65   839.4  659.37   960.7  689.83
  1031.5  709.64    1082  729.33  1162.9  767.71  1213.4   794.2    1264  825.05
#Mann= 3 , 0 , 0
       0     .08       0   614.7    .045       0   639.7     .08       0
Bank Sta=614.7,639.7
XS Rating Curve= 0 ,0
Exp/Cntr=0.3,0.1

Type RM Length L Ch R = 1 ,1252.5  ,471.5,478.2,483.9
XS GIS Cut Line= 3
     1538741.902      426495.362     1539169.968      426100.631
     1539578.219      425700.311
#Sta/Elev= 30
      10  828.58    60.2   797.2    80.3   786.1   120.5  765.46   130.5  760.92
   140.6  757.29   170.7     749   180.7  745.67   220.9  730.04     261  711.86
   341.3  673.25   381.5  656.01   401.6  649.89   491.9  630.88     502  628.95
   539.7  624.14   552.2  623.37   564.7  623.97   642.5  630.15   652.5  631.13
   662.5  632.99   752.8  660.51   833.1  683.59   883.2  698.89   933.4   718.9
  1013.6  753.19  1073.8  777.65  1083.8  782.83  1113.9   801.4  1154.1  820.54
#Mann= 3 , 0 , 0
       0     .08       0   539.7    .045       0   564.7     .08       0
Bank Sta=539.7,564.7
XS Rating Curve= 0 ,0
Exp/Cntr=0.3,0.1

Type RM Length L Ch R = 1 ,774.4   ,472.3,492.6,512.4
XS GIS Cut Line= 3
     1538914.975       426783.88     1539394.657      426520.881
     1539863.642      426241.655
#Sta/Elev= 30
    10.1  808.99    20.3  808.37    30.4  808.77    40.5  810.19    60.8  814.64
    70.9  814.59      81  812.56    91.2  808.61   141.8  785.45   182.3  768.16
   212.7  756.53   253.3  744.29   263.4  740.31   283.7  731.02   354.6  695.18
   476.1  640.45   496.4  632.94   516.7  629.29   534.6  624.92     547  622.96
   559.6  623.13   739.1  631.82   759.3  633.47   880.6  646.77   910.9  652.08
   931.1  656.89   971.6  667.43  1042.3  687.87  1062.5  691.75  1092.9  695.69
#Mann= 3 , 0 , 0
       0     .08       0   534.6    .045       0   559.6     .08       0
Bank Sta=534.6,559.6
XS Rating Curve= 0 ,0
Exp/Cntr=0.3,0.1

Type RM Length L Ch R = 1 ,281.8   ,176.1,179.8,184.9
XS GIS Cut Line= 3
     1538982.483      426851.542     1539522.363      426977.479
     1540071.157      427076.805
#Sta/Elev= 30
    10.1  758.26    80.6  745.93     121  739.54   231.8  719.52   272.1  714.94
   282.2  713.08   312.5  704.51   362.9  688.97   423.3  667.04   493.9  643.16
     504  637.51   514.1  629.67   524.1  625.14   541.9  621.16   554.4  619.98
   566.9  621.05   584.8  623.59   594.9  623.96   625.4  623.52   676.1  624.38
   767.3  627.07   828.2  629.35   949.8  637.56     960  639.12   970.1  642.79
  1000.5  658.53  1010.7  662.91  1020.8  666.69  1081.7  687.13  1112.1  697.83
#Mann= 3 , 0 , 0
    10.1     .08       0   541.9    .045       0   566.9     .08       0
#XS Ineff= 2 , 0
                          594.48          631.97
Permanent Ineff=
       F       F
Bank Sta=541.9,566.9
XS Rating Curve= 0 ,0
Exp/Cntr=0.3,0.1

Type RM Length L Ch R = 1 ,102     ,119.7,102,84.3
XS GIS Cut Line= 4
     1538938.859      426853.308     1539206.223      427048.941
     1539711.607      427241.313     1540115.915      427140.236
#Sta/Elev= 30
      10  757.01    60.2   738.2    80.3  731.33   130.5  717.11   210.8  692.68
     261  673.05   331.3  649.97   381.4  637.86   411.4  629.93   421.4  627.64
   441.4  625.15   491.5  623.14   561.6  622.77   571.6  622.15   589.2   619.6
   601.7  618.88   614.2  619.02   671.8  619.56     842  625.16   981.2  628.66
   991.1  629.15    1011  630.88  1050.7  634.72  1060.6  636.07  1070.5  638.07
  1080.4  640.76    1130  656.83  1249.1  697.69    1269  704.79  1288.8  712.33
#Mann= 3 , 0 , 0
      10     .08       0   589.2    .045       0   614.2     .08       0
#XS Ineff= 2 , 0
                          720.49           637.7
Permanent Ineff=
       F       F
Bank Sta=589.2,614.2
XS Rating Curve= 0 ,0
Exp/Cntr=0.3,0.1

Chan Stop Cuts=-1
Use User Specified Reach Order=0